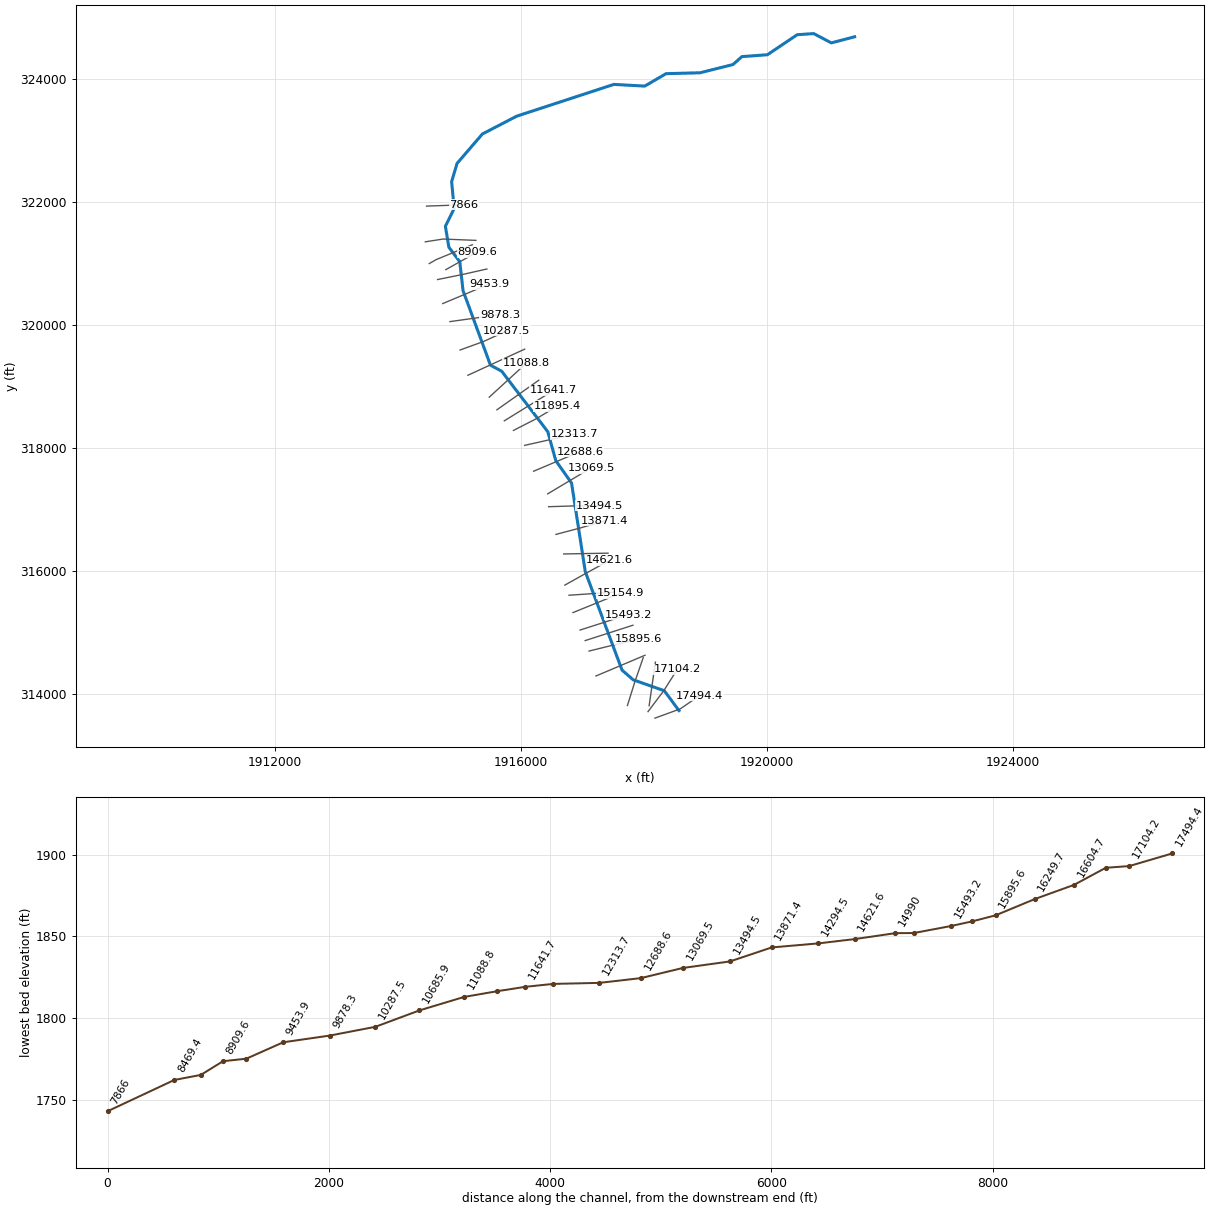
--- DnlpCrk.prj (project) ---

Proj Title=DnlpCrk
Current Plan=p01
Default Exp/Contr=0,0
English Units
Geom File=g01
Flow File=f01
Plan File=p01
BEGIN DESCRIPTION:
END DESCRIPTION:
DSS Export Rating Curves= 0
DSS Export Rating Curve Sorted= 0
DSS Export Volume Flow Curves= 0
DXF OffsetX= 0
DXF OffsetY= 0
DXF ScaleX= 0
DXF ScaleY= 0

--- DnlpCrk.p01 (plan) ---

Plan Title=Floodplain
Program Version=4.00
Geom File=g01
Flow File=f01
K Sum by GR=0
Std Step Tol=0.01
Critical Tol=0.01
Num of Std Step Trials=20
Max Error Tol=0.3
Flow Tol Ratio=0.001
Split Flow NTrial=30
Split Flow Tol=0.02
Split Flow Ratio=0.02
Log Output Level=0
Friction Slope Method=1
Unsteady Friction Slope Method=2
Unsteady Bridges Friction Slope Method=1
Global Log Level=0
CheckData=False
Run HTab=0
Run UNet=0
Run PostProcess=0
UNET Theta=0
UNET Theta Warmup=0
UNET ZTol=0
UNET ZSATol=0
UNET MxIter=0
UNET MaxInSteps=0
UNET DtIC=0
UNET DtMin=0
UNET MaxCRTS=0
UNET WFStab=0
UNET SFStab=0
UNET WFX=0
UNET SFX=0
UNET DSS MLevel=0
UNET DZMax Abort=0
UNET Convert EG Bridges=0
UNET Use Existing IB Tables=0
UNET Froude Limit=0
UNET Froude Power=0
Write IC File=0
Echo Input=False
Echo Output=False
Write Detailed=0

--- DnlpCrk.f01 (steady flow) ---

Flow Title=NFF Regression Equation
Program Version=4.10
Number of Profiles= 1
Profile Names=P100yr
River Rch & RM=DnlpCrk,Main            ,17494.4
543.8262
River Rch & RM=DnlpCrk,Main            ,14990
580.2913
River Rch & RM=DnlpCrk,Main            ,14621.6
728.5631
River Rch & RM=DnlpCrk,Main            ,14294.5
 730.461
River Rch & RM=DnlpCrk,Main            ,13871.4
869.5919
River Rch & RM=DnlpCrk,Main            ,11389.3
932.6044
River Rch & RM=DnlpCrk,Main            ,11088.8
1041.716
Boundary for River Rch & Prof#=DnlpCrk,Main            , 1
Up Type= 0
Dn Type= 1
Dn Known WS=1747.32
DSS Import GetInterval= 0
DSS Import GetPeak= 0
DSS Import FillOption= 0

--- DnlpCrk.g01 (geometry) ---

Geom Title=USGS 3m DEM
Program Version=4.00

River Reach=DnlpCrk     ,Main
Reach XY= 30
     1918569.212      313736.599     1918330.258      314060.004
     1917824.786      314237.067     1917643.541      314395.263
     1917046.404      315994.900     1916823.226      317435.562
     1916567.598      317798.051     1916437.560      318268.132
     1915689.662      319250.103     1915505.569      319350.342
     1915060.021      320561.768     1915006.911      321031.343
     1914829.536      321267.889     1914772.966      321606.879
     1914916.195      321895.941     1914874.529      322333.442
     1914963.070      322629.014     1915374.529      323106.879
     1915930.518      323395.941     1917511.248      323912.869
     1918013.513      323885.201     1918358.904      324087.348
     1918910.987      324101.671     1919447.445      324235.785
     1919591.977      324364.691     1920006.039      324394.640
     1920490.414      324720.160     1920758.643      324738.390
     1921045.102      324587.348     1921424.273      324686.845

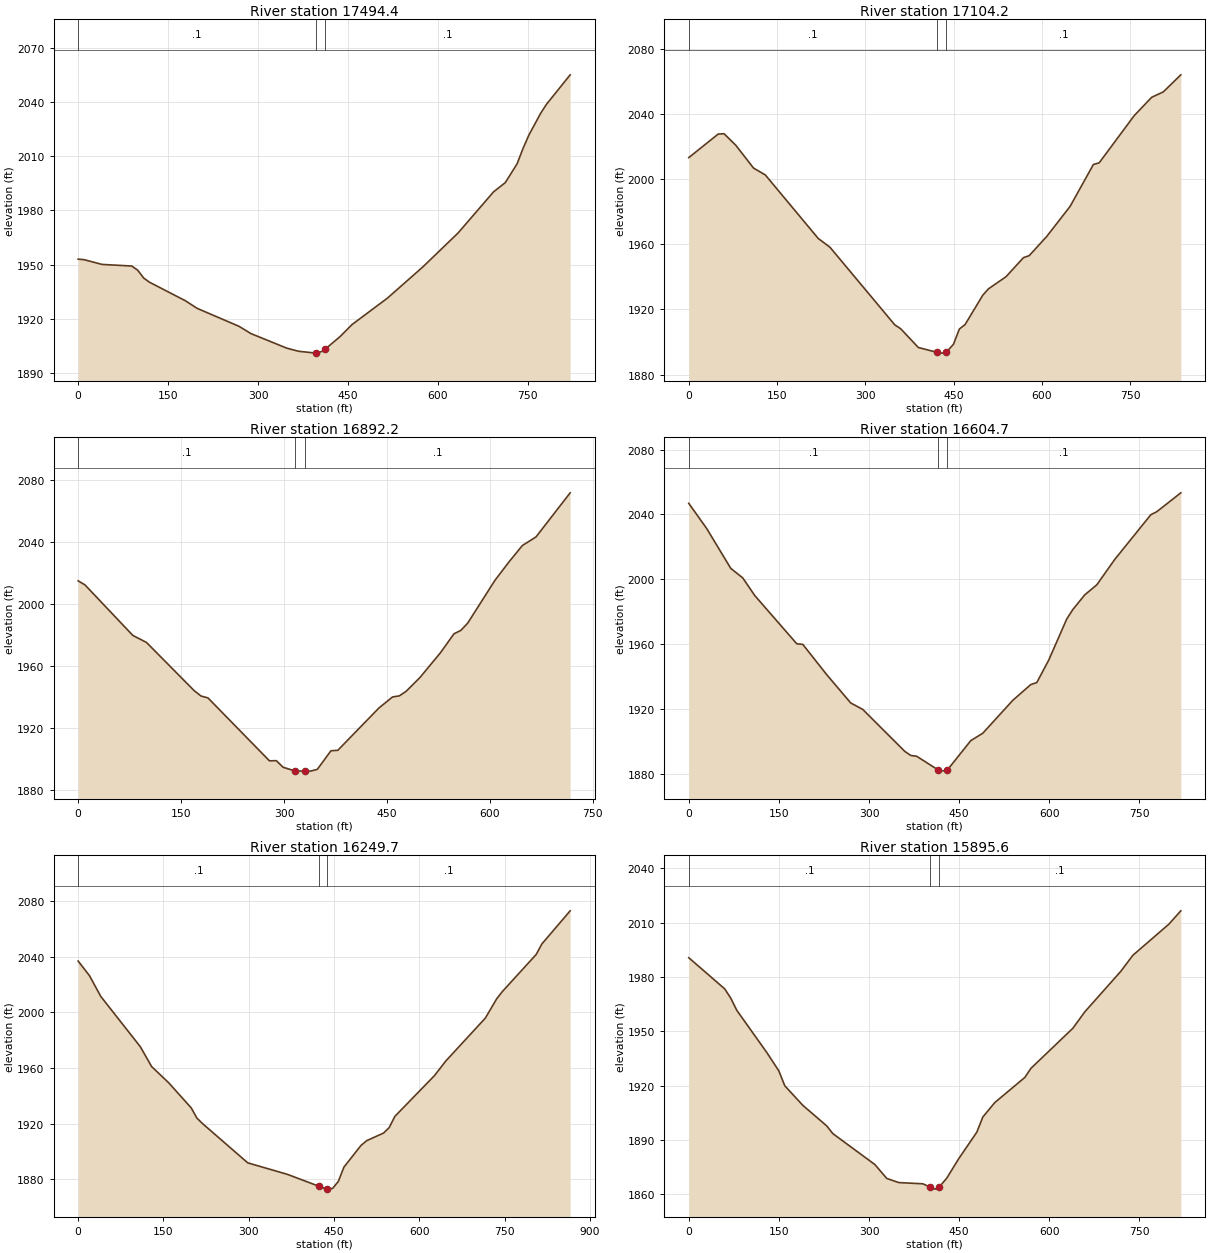
Type RM Length L Ch R = 1 ,17494.4,377.1,390.2,405.1
XS GIS Cut Line= 3
     1918178.894      313614.759     1918589.575      313764.574
     1918905.338      313982.035
#Sta/Elev= 30
       0 1953.03     9.9 1952.73    39.7 1950.10    89.4 1949.20    99.4 1946.89
   109.3 1942.54   119.2 1940.19   178.8 1929.96   198.7 1925.70   268.2 1915.79
   288.1 1911.75   347.7 1903.69   367.6 1901.93   396.7 1900.91   397.4 1900.90
   407.4 1901.92   411.7 1903.02   437.2 1910.18   456.8 1916.74   515.8 1931.39
   574.8 1948.68   633.8 1967.58   692.8 1990.33   712.4 1995.46   732.1 2005.90
   741.9 2014.34   751.7 2021.80   771.4 2033.92   781.2 2038.94   820.6 2055.24
#Mann= 3 , 0 , 0
       0     0.1       0   396.7   0.045       0   411.7     0.1       0
Bank Sta=   396.7,   411.7
Exp/Cntr=0.3,0.1

Type RM Length L Ch R = 1 ,17104.2,200.1,211.4,221
XS GIS Cut Line= 3
     1918066.192      313720.067     1918324.462      314063.682
     1918541.957      314406.403
#Sta/Elev= 30
       0 2013.13    50.0 2027.60    60.0 2027.77    80.0 2020.66   110.0 2006.70
   130.0 2002.50   219.9 1963.51   239.9 1958.10   349.9 1910.50   359.9 1908.11
   389.9 1896.60   422.4 1893.53   429.8 1893.13   437.4 1893.65   449.6 1898.56
   459.6 1907.90   469.4 1910.68   499.2 1928.57   509.1 1932.60   538.8 1940.01
   568.5 1951.71   578.4 1953.00   608.1 1964.77   647.7 1983.17   687.3 2008.90
   697.2 2009.95   756.6 2038.88   786.3 2050.15   806.1 2053.47   835.8 2063.94
#Mann= 3 , 0 , 0
       0     0.1       0   422.4   0.045       0   437.4     0.1       0
Bank Sta=   422.4,   437.4
Exp/Cntr=0.3,0.1

Type RM Length L Ch R = 1 ,16892.2,291.6,287.6,283.2
XS GIS Cut Line= 2
     1918083.906      313814.919     1918186.344      314524.532
#Sta/Elev= 30
       0 2015.07    10.0 2012.42    79.7 1979.78    99.6 1975.25   169.3 1944.00
   179.2 1940.59   189.2 1939.40   278.8 1898.74   288.8 1898.85   298.7 1894.58
   316.3 1892.16   331.3 1892.10   338.6 1892.09   348.5 1893.21   368.4 1905.24
   378.4 1905.55   438.2 1932.84   458.1 1940.01   468.0 1940.72   478.0 1943.68
   497.9 1952.48   527.8 1968.50   547.7 1980.83   557.6 1983.00   567.6 1987.68
   607.4 2015.39   627.4 2027.03   647.3 2037.86   667.2 2043.42   717.0 2071.93
#Mann= 3 , 0 , 0
       0     0.1       0   316.3   0.045       0   331.3     0.1       0
Bank Sta=   316.3,   331.3
Exp/Cntr=0.3,0.1

Type RM Length L Ch R = 1 ,16604.7,374.1,354.8,335.8
XS GIS Cut Line= 3
     1917731.312      313819.402     1917853.781      314210.135
     1917988.191      314597.090
#Sta/Elev= 30
       0 2046.85    30.0 2031.21    69.9 2006.72    89.9 2000.82   109.9 1989.92
   179.8 1960.18   189.8 1959.82   229.7 1941.10   269.7 1923.63   289.6 1919.69
   359.5 1893.82   369.5 1891.29   379.5 1890.76   415.2 1882.31   419.5 1881.60
   430.2 1882.17   469.4 1900.41   489.4 1904.97   539.4 1925.30   569.3 1935.00
   579.3 1936.24   599.3 1950.17   629.3 1975.55   639.3 1981.30   659.2 1990.37
   679.2 1996.55   709.2 2012.28   769.2 2039.84   779.2 2041.72   819.1 2053.34
#Mann= 3 , 0 , 0
       0     0.1       0   415.2   0.045       0   430.2     0.1       0
Bank Sta=   415.2,   430.2
Exp/Cntr=0.3,0.1

Type RM Length L Ch R = 1 ,16249.7,357.6,354.1,350.2
XS GIS Cut Line= 2
     1917219.706      314299.169     1918016.856      314636.282
#Sta/Elev= 30
       0 2036.81    19.9 2026.33    39.8 2011.40   109.4 1975.24   129.3 1960.97
   159.2 1949.38   199.0 1931.25   208.9 1923.97   218.9 1919.98   298.4 1891.78
   368.1 1883.53   423.1 1875.04   437.7 1872.91   438.1 1872.93   447.7 1873.47
   457.6 1878.39   467.6 1888.76   497.4 1904.22   507.4 1907.70   537.2 1913.20
   547.2 1917.14   557.1 1925.17   626.7 1954.44   646.6 1964.93   716.3 1995.82
   736.2 2009.66   746.1 2014.83   805.8 2041.59   815.8 2049.14   865.5 2072.90
#Mann= 3 , 0 , 0
       0     0.1       0   423.1   0.045       0   438.1     0.1       0
Bank Sta=   423.1,   438.1
Exp/Cntr=0.3,0.1

Type RM Length L Ch R = 1 ,15895.6,209.6,211.2,213
XS GIS Cut Line= 3
     1917108.234      314704.581     1917505.812      314802.899
     1917904.733      314895.332
#Sta/Elev= 30
       0 1990.59    59.9 1973.38    69.9 1968.26    79.9 1961.58   129.9 1938.28
   149.8 1928.22   159.8 1919.95   189.8 1909.16   229.8 1897.76   239.7 1893.58
   309.7 1876.51   329.6 1868.82   349.6 1866.54   389.6 1865.87   402.1 1864.00
   409.6 1862.93   417.1 1864.16   429.5 1869.03   449.5 1879.81   479.5 1894.38
   489.4 1902.69   509.4 1910.70   559.4 1924.56   569.4 1929.52   639.3 1951.67
   659.2 1960.73   719.2 1983.12   739.1 1991.90   799.1 2009.09   819.0 2016.46
#Mann= 3 , 0 , 0
       0     0.1       0   402.1   0.045       0   417.1     0.1       0
Bank Sta=   402.1,   417.1
Exp/Cntr=0.3,0.1

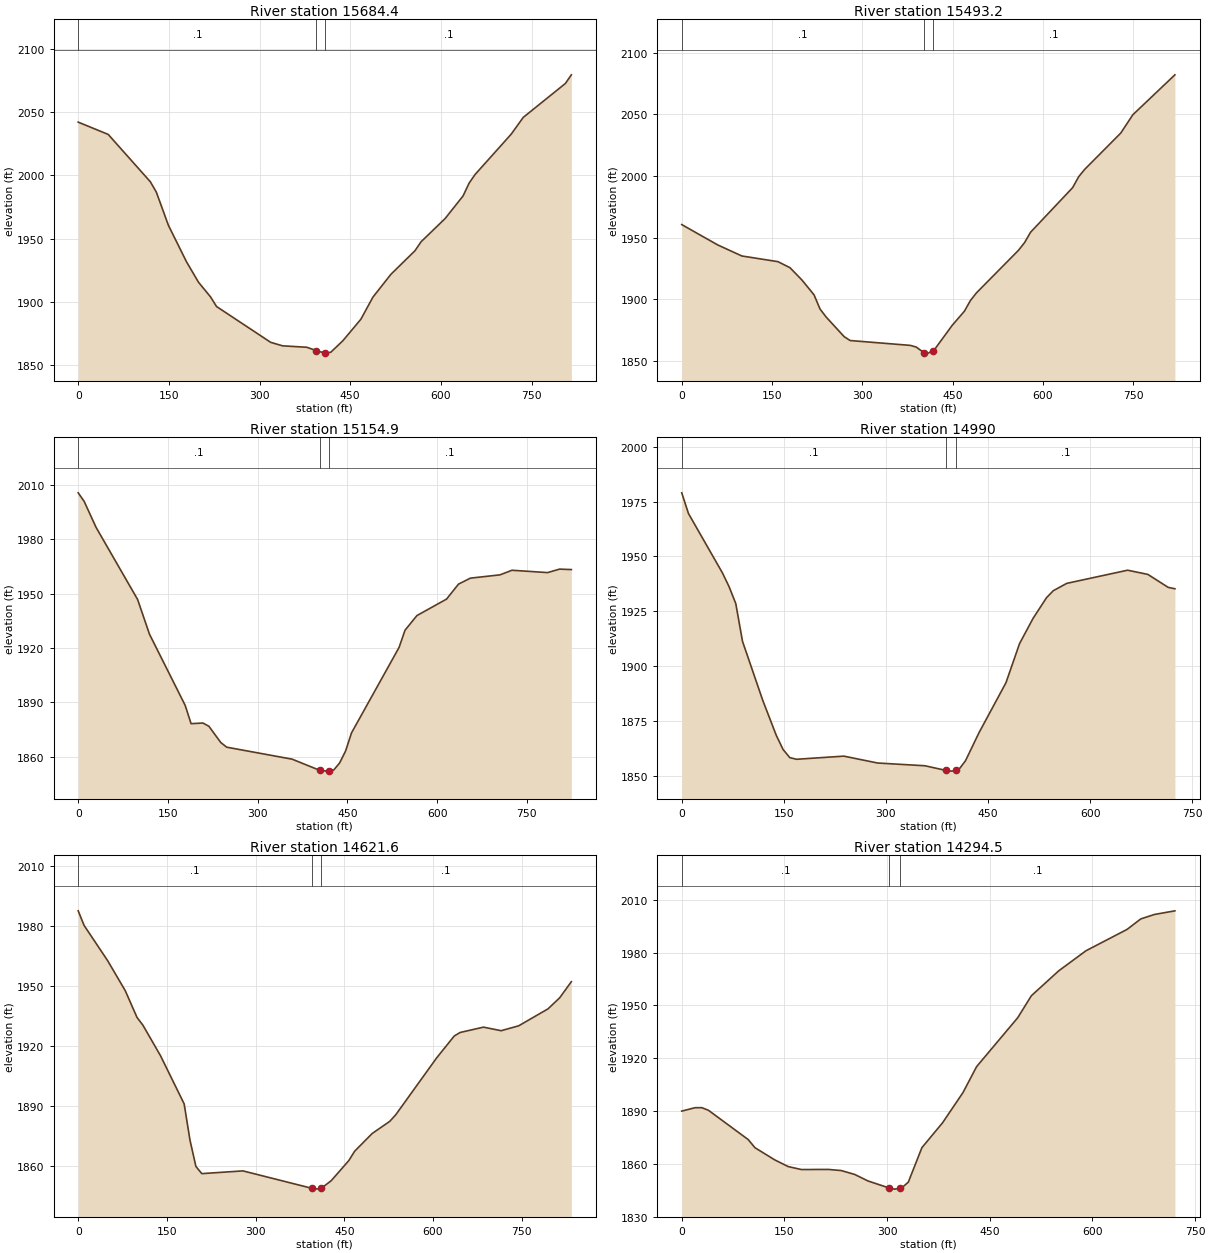
Type RM Length L Ch R = 1 ,15684.4,191.3,191.2,191.1
XS GIS Cut Line= 2
     1917044.631      314874.682     1917821.294      315124.257
#Sta/Elev= 30
       0 2042.19    49.7 2032.44   119.4 1994.92   129.3 1986.70   149.2 1960.50
   179.1 1931.64   199.0 1915.39   218.9 1903.80   228.8 1896.18   318.4 1867.79
   338.2 1865.01   378.0 1863.89     394 1861.26   407.9 1859.24     409 1859.32
   417.8 1859.94   437.7 1868.99   467.6 1886.07   487.5 1903.56   517.3 1921.67
   557.1 1940.32   567.1 1947.39   606.9 1965.80   636.7 1983.75   646.6 1993.84
   656.6 2000.76   716.3 2032.67   736.2 2045.94   805.8 2072.76   815.8 2079.65
#Mann= 3 , 0 , 0
       0     0.1       0     394   0.045       0     409     0.1       0
Bank Sta=     394,     409
Exp/Cntr=0.3,0.1

Type RM Length L Ch R = 1 ,15493.2,336.5,338.2,340
XS GIS Cut Line= 3
     1916962.668      315046.262     1917352.686      315171.068
     1917742.704      315295.873
#Sta/Elev= 30
       0 1960.63    59.9 1944.09    99.9 1935.17   159.8 1930.56   179.8 1925.65
   199.8 1915.58   219.7 1903.66   229.7 1892.14   239.7 1885.73   269.7 1869.77
   279.7 1866.60   379.5 1862.68   389.5 1861.29     402 1856.82   409.5 1856.39
     417 1858.44   419.5 1859.12   449.4 1879.08   469.4 1890.36   479.4 1899.02
   489.4 1905.24   559.3 1939.81   569.3 1945.98   579.3 1954.43   649.2 1990.61
   659.2 1999.44   669.2 2005.41   729.1 2034.85   749.1 2049.66   819.0 2082.07
#Mann= 3 , 0 , 0
       0     0.1       0     402   0.045       0     417     0.1       0
Bank Sta=     402,     417
Exp/Cntr=0.3,0.1

Type RM Length L Ch R = 1 ,15154.9,172,164.9,157.7
XS GIS Cut Line= 2
     1916847.159      315329.784     1917610.940      315640.092
#Sta/Elev= 30
       0 2005.65     9.9 2000.98    29.8 1986.64    99.3 1946.80   119.2 1927.62
   178.8 1888.38   188.7 1878.26   208.6 1878.61   218.5 1876.82   238.4 1867.84
   248.3 1865.28   357.6 1858.67   403.8 1852.51   417.2 1852.07   418.8 1852.16
   427.1 1852.65   437.0 1856.58   447.0 1863.19   456.9 1873.19   536.4 1920.34
   546.3 1929.82   566.2 1937.90   615.8 1947.02   635.7 1955.26   655.6 1958.56
   705.2 1960.39   725.1 1962.92   784.7 1961.63   804.6 1963.55   824.4 1963.30
#Mann= 3 , 0 , 0
       0     0.1       0   403.8   0.045       0   418.8     0.1       0
Bank Sta=   403.8,   418.8
Exp/Cntr=0.3,0.1

Type RM Length L Ch R = 1 ,14990,358.4,368.4,378.4
XS GIS Cut Line= 2
     1916782.368      315611.592     1917505.251      315660.832
#Sta/Elev= 30
       0 1979.02     9.9 1969.57    59.6 1942.59    69.5 1936.24    79.4 1928.48
    89.3 1911.24   119.1 1884.27   139.0 1868.28   148.9 1861.90   158.8 1858.18
   168.7 1857.43   238.2 1858.86   287.8 1855.72   357.3 1854.47   387.9 1852.37
   397.0 1852.02   402.9 1852.39   406.9 1852.64   416.9 1856.75   436.7 1869.51
   476.4 1892.37   496.3 1910.18   516.1 1921.68   536.0 1931.18   545.9 1934.35
   565.8 1937.71   655.1 1943.71   684.9 1941.79   714.6 1935.90   724.6 1935.24
#Mann= 3 , 0 , 0
       0     0.1       0   387.9   0.045       0   402.9     0.1       0
Bank Sta=   387.9,   402.9
Exp/Cntr=0.3,0.1

Type RM Length L Ch R = 1 ,14621.6,338.3,327.1,315.9
XS GIS Cut Line= 3
     1916715.159      315776.616     1917088.797      315985.307
     1917445.090      316180.320
#Sta/Elev= 30
       0 1987.73    10.0 1980.41    49.8 1962.78    79.6 1947.74    99.5 1934.34
   109.5 1930.44   139.3 1915.13   179.2 1891.07   189.1 1872.85   199.1 1859.73
   209.0 1856.13   278.7 1857.50   395.8 1848.74   408.1 1848.37   410.8 1848.70
   428.0 1852.62   457.7 1862.66   467.6 1867.36   497.3 1876.24   527.0 1882.32
   536.9 1885.54   606.3 1914.10   636.0 1925.04   645.9 1926.81   685.5 1929.48
   715.3 1927.70   745.0 1930.15   794.5 1938.62   814.3 1944.16   834.1 1952.25
#Mann= 3 , 0 , 0
       0     0.1       0   395.8   0.045       0   410.8     0.1       0
Bank Sta=   395.8,   410.8
Exp/Cntr=0.3,0.1

Type RM Length L Ch R = 1 ,14294.5,417.8,423.1,429
XS GIS Cut Line= 3
     1916696.124      316282.145     1917007.057      316288.198
     1917416.498      316295.196
#Sta/Elev= 30
       0 1890.03    19.4 1891.95    29.2 1891.98    38.9 1890.53    97.2 1873.84
   106.9 1869.27   136.1 1862.29   155.5 1858.55   174.9 1856.85   213.8 1856.93
   233.2 1856.27   252.7 1854.07   272.1 1850.38   303.5 1846.32   311.0 1845.74
   318.5 1846.18   321.0 1846.33   331.0 1849.68   350.9 1869.30   380.9 1883.32
   410.9 1900.55   430.8 1915.28   490.8 1943.00   510.8 1955.52   550.7 1969.63
   590.6 1981.05   650.6 1993.16   670.6 1999.11   690.5 2001.63   720.5 2003.71
#Mann= 3 , 0 , 0
       0     0.1       0   303.5   0.045       0   318.5     0.1       0
Bank Sta=   303.5,   318.5
Exp/Cntr=0.3,0.1

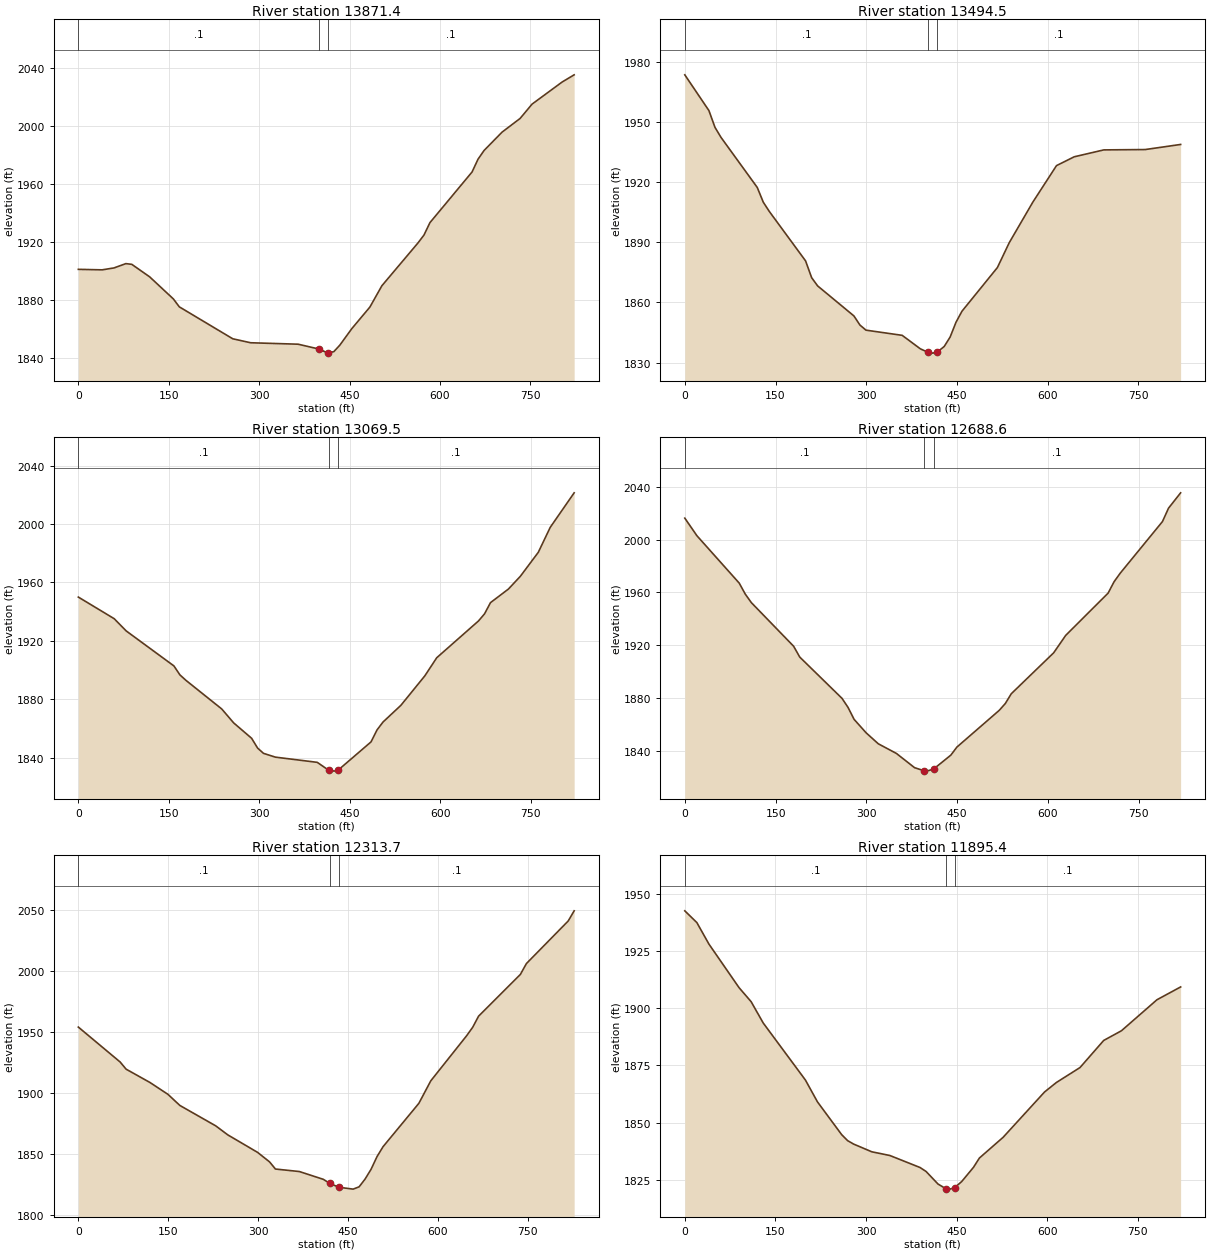
Type RM Length L Ch R = 1 ,13871.4,382,376.9,371
XS GIS Cut Line= 3
     1916570.247      316600.310     1916970.431      316706.023
     1917362.803      316820.465
#Sta/Elev= 30
       0 1901.15    39.4 1900.80    59.1 1902.12    78.8 1905.10    88.7 1904.61
   118.3 1895.98   157.7 1880.69   167.5 1875.24   256.2 1853.16   285.8 1850.42
   364.6 1849.42   399.7 1846.03   413.9 1843.25   414.7 1843.33   423.9 1844.29
   433.8 1848.74   453.8 1860.22   483.7 1875.07   503.6 1889.81   563.4 1919.35
   573.4 1924.82   583.4 1933.46   653.2 1968.42   663.1 1977.24   673.1 1983.27
   703.0 1995.97   732.9 2005.41   752.8 2015.34   802.7 2030.61   822.6 2035.57
#Mann= 3 , 0 , 0
       0     0.1       0   399.7   0.045       0   414.7     0.1       0
Bank Sta=   399.7,   414.7
Exp/Cntr=0.3,0.1

Type RM Length L Ch R = 1 ,13494.5,413.4,424.8,436.6
XS GIS Cut Line= 3
     1916450.328      317050.302     1916859.484      317062.796
     1917269.791      317069.642
#Sta/Elev= 30
       0 1973.48    39.9 1955.64    49.9 1947.28    59.9 1942.26   119.8 1917.31
   129.8 1909.93   139.8 1905.31   199.7 1880.67   209.7 1872.31   219.6 1868.21
   279.6 1853.23   289.5 1848.70   299.5 1846.14   359.4 1843.55   389.4 1836.83
   401.8 1835.13   409.4 1834.68   416.8 1835.07   428.9 1838.01   438.7 1842.73
   448.4 1850.11   458.2 1855.57   516.8 1877.36   536.4 1889.77   575.4 1910.00
   614.5 1928.20   643.8 1932.60   692.7 1936.04   761.1 1936.21   819.7 1938.75
#Mann= 3 , 0 , 0
       0     0.1       0   401.8   0.045       0   416.8     0.1       0
Bank Sta=   401.8,   416.8
Exp/Cntr=0.3,0.1

Type RM Length L Ch R = 1 ,13069.5,384,380.8,377.5
XS GIS Cut Line= 2
     1916435.649      317259.204     1917141.091      317680.313
#Sta/Elev= 30
       0 1949.95    59.4 1935.15    79.2 1926.80   158.4 1902.78   168.3 1896.66
   178.2 1892.94   237.6 1873.30   257.4 1863.74   287.1 1853.21   297.0 1846.53
   306.8 1842.88   326.6 1840.27   395.9 1836.71   415.4 1831.15   425.6 1830.69
   430.4 1831.34   485.0 1850.72   494.9 1858.89   504.8 1864.30   534.5 1875.78
   574.1 1895.94   593.9 1908.39   663.2 1933.64   673.1 1938.46   683.0 1946.15
   712.7 1955.46   732.5 1964.22   762.2 1980.64   782.0 1997.76   821.6 2021.39
#Mann= 3 , 0 , 0
       0     0.1       0   415.4   0.045       0   430.4     0.1       0
Bank Sta=   415.4,   430.4
Exp/Cntr=0.3,0.1

Type RM Length L Ch R = 1 ,12688.6,378.6,374.7,370.8
XS GIS Cut Line= 3
     1916206.490      317626.629     1916583.695      317786.023
     1916960.901      317945.417
#Sta/Elev= 30
       0 2016.21    20.0 2002.89    89.9 1966.96    99.9 1958.62   109.9 1952.19
   179.8 1919.09   189.8 1910.94   259.7 1879.60   269.7 1872.70   279.7 1863.66
   299.6 1853.45   319.6 1845.18   349.6 1837.84   379.5 1827.08   395.9 1824.63
   399.5 1824.45   410.9 1825.99   439.5 1836.60   449.4 1842.65   519.4 1870.52
   529.4 1875.68   539.3 1883.11   609.3 1914.13   629.2 1927.34   699.2 1959.36
   709.1 1968.01   719.1 1974.40   789.0 2013.61   799.0 2023.74   819.0 2035.39
#Mann= 3 , 0 , 0
       0     0.1       0   395.9   0.045       0   410.9     0.1       0
Bank Sta=   395.9,   410.9
Exp/Cntr=0.3,0.1

Type RM Length L Ch R = 1 ,12313.7,411.3,418.1,425.2
XS GIS Cut Line= 2
     1916061.910      318047.174     1916869.141      318228.384
#Sta/Elev= 30
       0 1954.07    69.8 1925.49    79.7 1919.66   119.6 1908.73   149.5 1899.07
   169.4 1889.98   229.3 1873.27   249.2 1865.96   299.0 1851.62   319.0 1843.85
   328.9 1837.96   368.8 1835.92   408.7 1829.56   419.5 1826.25   434.5 1823.08
   458.5 1821.53   468.5 1823.42   478.4 1829.72   488.4 1837.72   498.4 1848.16
   508.4 1856.22   568.2 1891.71   588.1 1910.12   647.9 1947.00   657.9 1953.82
   667.8 1962.99   737.6 1997.16   747.6 2006.00   817.4 2040.87   827.3 2049.16
#Mann= 3 , 0 , 0
       0     0.1       0   419.5   0.045       0   434.5     0.1       0
Bank Sta=   419.5,   434.5
Exp/Cntr=0.3,0.1

Type RM Length L Ch R = 1 ,11895.4,253.5,253.8,253.9
XS GIS Cut Line= 3
     1915879.371      318289.628     1916243.691      318476.146
     1916596.849      318687.045
#Sta/Elev= 30
       0 1942.49    20.0 1937.34    39.9 1927.98    89.8 1908.92   109.8 1902.79
   129.8 1893.48   199.6 1868.57   219.6 1859.01   259.6 1844.71   269.5 1842.08
   279.5 1840.57   309.5 1837.21   339.4 1835.59   389.3 1830.35   399.3 1828.62
   419.1 1823.12   431.9 1821.12   438.7 1820.90   446.9 1821.60   458.3 1824.22
   477.8 1830.43   487.6 1834.49   526.8 1843.53   595.4 1863.34   615.0 1867.49
   654.1 1874.02   693.3 1885.86   722.7 1890.10   781.4 1903.63   820.6 1909.24
#Mann= 3 , 0 , 0
       0     0.1       0   431.9   0.045       0   446.9     0.1       0
Bank Sta=   431.9,   446.9
Exp/Cntr=0.3,0.1

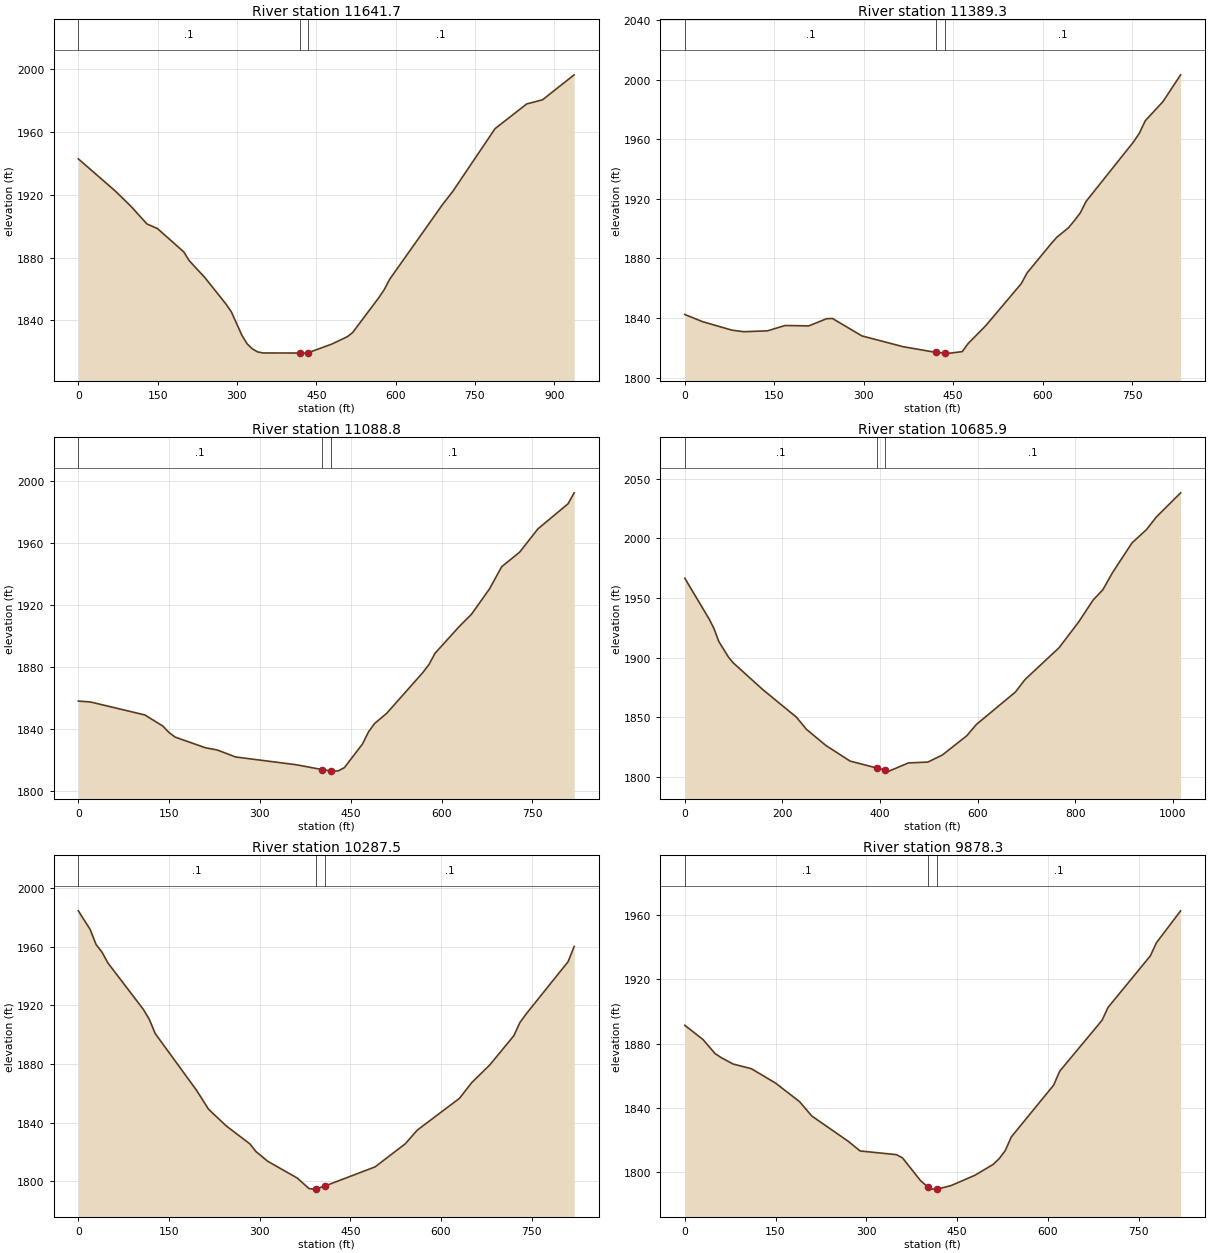
Type RM Length L Ch R = 1 ,11641.7,249.4,252,254.6
XS GIS Cut Line= 2
     1915730.843      318446.051     1916528.596      318938.664
#Sta/Elev= 30
       0 1942.88    69.8 1922.42    99.7 1912.58   129.7 1901.43   149.6 1898.48
   199.5 1883.57   209.5 1878.08   239.4 1867.20   279.3 1850.32   289.3 1845.45
   309.2 1830.53   319.2 1825.02   329.2 1821.79   339.1 1819.86   349.1 1819.20
   419.2 1819.15   428.9 1819.09   434.2 1819.32   478.8 1824.78   508.7 1829.56
   518.7 1832.19   568.5 1854.56   578.5 1859.57   588.5 1866.04   688.2 1913.54
   708.2 1922.21   788.0 1962.12   847.8 1977.87   877.8 1980.52   937.6 1996.43
#Mann= 3 , 0 , 0
       0     0.1       0   419.2   0.045       0   434.2     0.1       0
Bank Sta=   419.2,   434.2
Exp/Cntr=0.3,0.1

Type RM Length L Ch R = 1 ,11389.3,298.3,300.5,302.6
XS GIS Cut Line= 2
     1915610.757      318625.191     1916289.792      319104.625
#Sta/Elev= 30
       0 1842.35    29.7 1837.56    79.2 1831.82    99.0 1830.80   138.5 1831.38
   168.2 1834.97   207.8 1834.70   237.5 1839.49   247.4 1839.70   296.9 1827.98
   366.1 1820.72   421.3 1816.91   436.3 1816.50   445.3 1816.42   465.1 1817.44
   475.0 1822.85   504.7 1834.94   564.0 1863.06   574.0 1870.36   613.5 1889.58
   623.4 1894.13   643.2 1900.59   653.1 1905.36   663.0 1910.58   672.9 1918.38
   752.1 1958.14   762.0 1964.02   771.9 1972.40   801.5 1985.21   831.2 2003.24
#Mann= 3 , 0 , 0
       0     0.1       0   421.3   0.045       0   436.3     0.1       0
Bank Sta=   421.3,   436.3
Exp/Cntr=0.3,0.1

Type RM Length L Ch R = 1 ,11088.8,409.6,402.6,395.7
XS GIS Cut Line= 3
     1915486.101      318830.522     1915788.138      319107.043
     1916090.176      319383.563
#Sta/Elev= 30
       0 1858.09    20.0 1857.52   109.9 1849.13   139.8 1841.91   149.8 1837.80
   159.8 1834.86   209.7 1828.00   229.7 1826.52   259.7 1822.03   359.6 1817.04
     402 1813.95     417 1813.02   419.5 1812.90   429.5 1813.06   439.5 1815.15
   469.4 1830.43   479.4 1838.27   489.4 1843.63   509.4 1850.20   569.3 1876.61
   579.3 1881.77   589.3 1888.97   629.2 1906.19   649.2 1913.99   679.2 1930.46
   699.2 1944.72   729.1 1954.22   759.1 1969.16   809.0 1985.40   819.0 1992.43
#Mann= 3 , 0 , 0
       0     0.1       0     402   0.045       0     417     0.1       0
Bank Sta=     402,     417
Exp/Cntr=0.3,0.1

Type RM Length L Ch R = 1 ,10685.9,400.3,398.4,397.5
XS GIS Cut Line= 2
     1915138.517      319186.161     1916061.910      319610.771
#Sta/Elev= 30
       0 1966.63    49.8 1932.44    59.8 1924.37    69.8 1913.43    89.7 1900.30
    99.6 1895.45   159.4 1873.27   229.2 1849.82   249.1 1839.83   289.0 1826.24
   338.8 1813.09   394.7 1807.14   409.7 1805.52   418.5 1804.65   458.4 1811.54
   498.2 1812.25   528.1 1818.24   577.9 1834.33   597.8 1843.90   677.6 1871.04
   697.5 1881.62   767.2 1908.29   807.1 1929.78   837.0 1948.35   856.9 1956.94
   876.8 1971.39   916.7 1996.32   946.6 2007.58   966.5 2018.02  1016.3 2038.33
#Mann= 3 , 0 , 0
       0     0.1       0   394.7   0.045       0   409.7     0.1       0
Bank Sta=   394.7,   409.7
Exp/Cntr=0.3,0.1

Type RM Length L Ch R = 1 ,10287.5,413.9,409.1,403.4
XS GIS Cut Line= 3
     1915012.314      319596.880     1915398.765      319737.239
     1915770.762      319907.737
#Sta/Elev= 30
       0 1984.48    19.6 1971.75    29.4 1961.47    39.2 1956.27    49.0 1948.89
   107.7 1917.17   117.5 1910.37   127.3 1900.70   195.8 1861.92   215.4 1849.15
   244.7 1837.75   283.9 1825.46   293.7 1820.32   313.3 1813.62   362.2 1802.17
   381.8 1794.93   391.6 1794.60   392.8 1794.72   407.8 1796.70   491.0 1809.78
   540.9 1825.51   560.9 1834.89   630.7 1856.56   650.7 1867.17   680.6 1879.25
   720.6 1899.27   730.5 1908.14   740.5 1913.87   810.4 1949.81   820.4 1960.11
#Mann= 3 , 0 , 0
       0     0.1       0   392.8   0.045       0   407.8     0.1       0
Bank Sta=   392.8,   407.8
Exp/Cntr=0.3,0.1

Type RM Length L Ch R = 1 ,9878.3,418.3,424.2,430.1
XS GIS Cut Line= 2
     1914847.091      320057.944     1915658.540      320171.854
#Sta/Elev= 30
       0 1891.37    30.0 1882.52    50.0 1873.74    60.0 1871.24    79.9 1867.21
   109.9 1864.32   149.9 1855.36   189.9 1843.70   209.8 1834.85   269.8 1819.15
   289.8 1813.04   349.8 1810.75   359.7 1808.76   389.7 1794.50   402.1 1790.45
   409.7 1789.26   417.1 1789.26   439.7 1791.42   479.6 1797.92   509.6 1804.66
   519.6 1808.28   529.6 1813.26   539.6 1821.79   609.6 1854.09   619.6 1862.76
   689.5 1894.45   699.5 1902.52   769.4 1934.65   779.4 1942.80   819.4 1962.69
#Mann= 3 , 0 , 0
       0     0.1       0   402.1   0.045       0   417.1     0.1       0
Bank Sta=   402.1,   417.1
Exp/Cntr=0.3,0.1

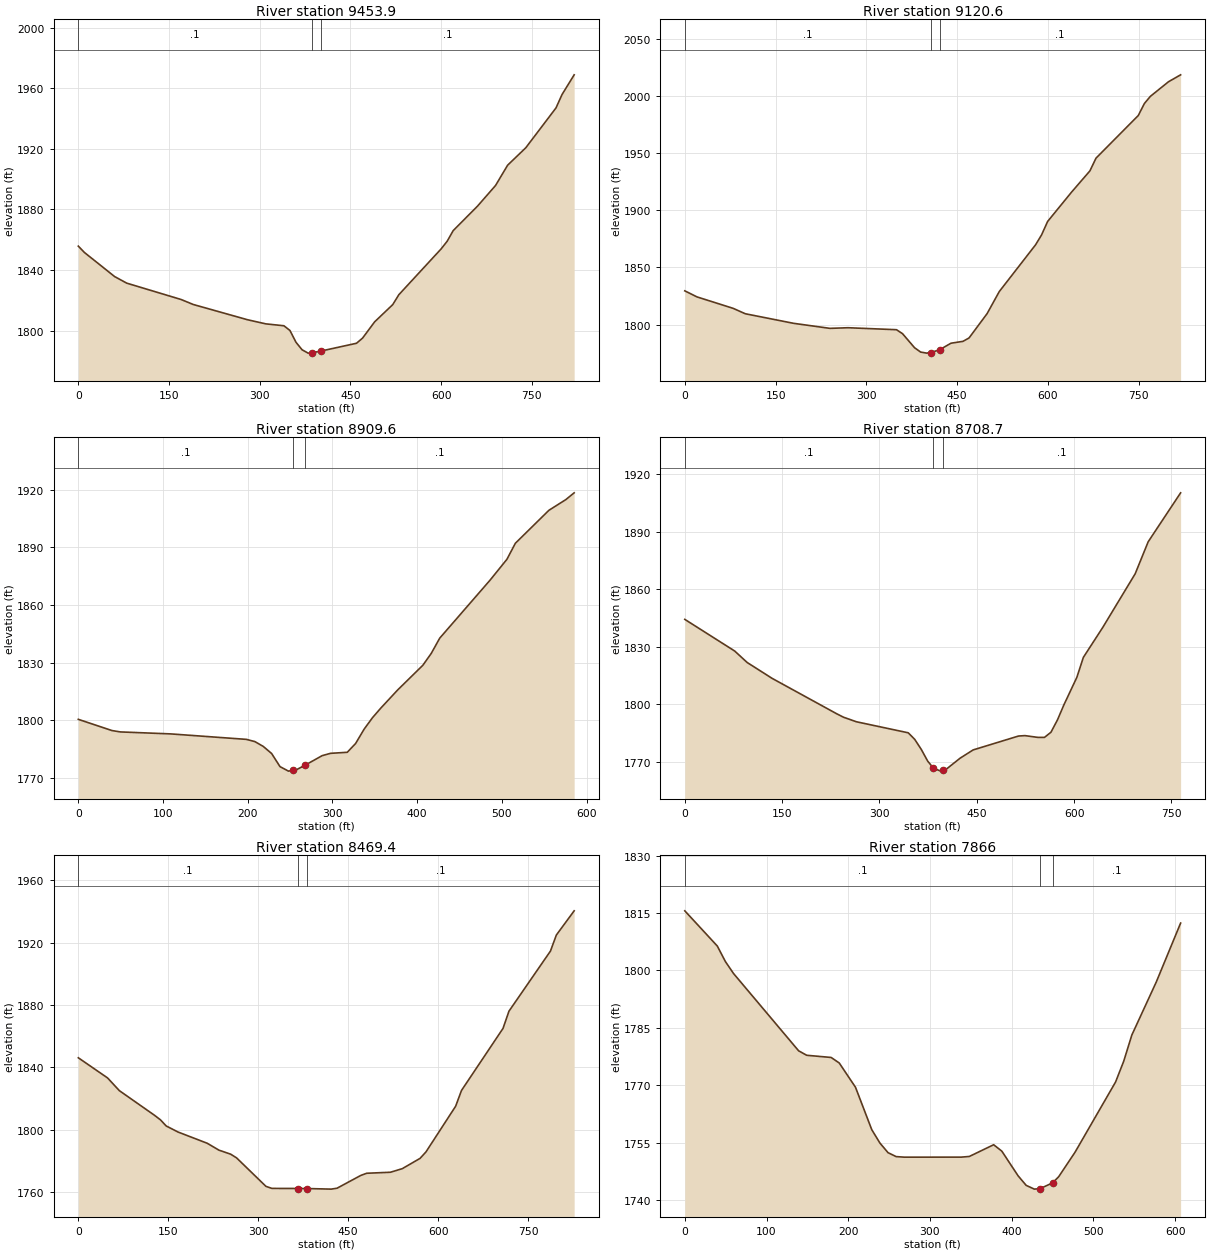
Type RM Length L Ch R = 1 ,9453.9,337.5,333,328.9
XS GIS Cut Line= 2
     1914730.226      320351.124     1915486.126      320668.458
#Sta/Elev= 30
       0 1855.72    10.0 1851.57    60.0 1835.64    80.0 1831.30   170.0 1820.49
   190.0 1817.21   279.9 1807.12   309.9 1804.42   339.9 1803.16   349.9 1800.05
   359.9 1792.26   369.9 1787.33   379.9 1785.10     386 1785.28     401 1786.46
   459.9 1791.60   469.9 1794.99   489.9 1805.74   519.9 1817.15   529.9 1823.64
   599.9 1853.92   609.9 1858.99   619.8 1865.97   659.8 1882.04   689.8 1895.74
   709.8 1909.15   739.8 1920.65   789.8 1946.97   799.8 1955.83   819.8 1968.81
#Mann= 3 , 0 , 0
       0     0.1       0     386   0.045       0     401     0.1       0
Bank Sta=     386,     401
Exp/Cntr=0.3,0.1

Type RM Length L Ch R = 1 ,9120.6,203.9,211,217.7
XS GIS Cut Line= 3
     1914646.239      320741.639     1915047.743      320822.810
     1915447.164      320913.002
#Sta/Elev= 30
       0 1829.52    20.0 1824.25    79.9 1814.21    99.9 1809.49   179.8 1801.11
   239.8 1796.71   269.8 1797.26   349.7 1795.53   359.7 1792.06   379.6 1779.75
   389.6 1775.97   399.6 1775.05     406 1775.52     421 1778.00   439.6 1783.70
   459.6 1785.36   469.6 1788.33   499.5 1809.67   519.5 1828.88   579.4 1869.73
   589.4 1878.45   599.4 1890.21   639.3 1916.09   669.3 1934.48   679.3 1945.55
   749.2 1982.88   759.2 1993.33   769.2 1999.65   799.1 2012.39   819.1 2018.44
#Mann= 3 , 0 , 0
       0     0.1       0     406   0.045       0     421     0.1       0
Bank Sta=     406,     421
Exp/Cntr=0.3,0.1

Type RM Length L Ch R = 1 ,8909.6,203.9,200.8,197.9
XS GIS Cut Line= 2
     1914780.296      320902.257     1915290.505      321189.315
#Sta/Elev= 30
       0 1800.46    39.7 1794.62    49.6 1793.91   109.2 1792.87   198.4 1790.03
   208.4 1788.88   218.3 1786.37   228.2 1782.68   238.1 1775.85   248.1 1773.50
   252.9 1773.91   258.0 1774.34   267.9 1776.63   287.8 1781.54   297.7 1782.76
   317.5 1783.30   327.4 1787.89   337.4 1795.33   347.3 1801.31   357.2 1806.34
   377.0 1815.73   406.8 1828.62   416.7 1834.79   426.7 1842.72   486.2 1872.94
   506.0 1883.74   516.0 1892.10   555.6 1909.26   575.5 1914.80   585.4 1918.35
#Mann= 3 , 0 , 0
       0     0.1       0   252.9   0.045       0   267.9     0.1       0
Bank Sta=   252.9,   267.9
Exp/Cntr=0.3,0.1

Type RM Length L Ch R = 1 ,8708.7,248.7,239,229.3
XS GIS Cut Line= 3
     1914510.945      321001.189     1914627.948      321067.669
     1915210.309      321306.995
#Sta/Elev= 30
       0 1844.34    76.9 1827.81    96.1 1821.83   134.6 1813.53   234.5 1794.98
   244.5 1793.27   264.5 1790.87   344.4 1785.11   354.4 1781.68   364.4 1776.48
   374.4 1770.32   383.3 1766.64   394.4 1765.10   398.3 1765.64   404.4 1766.48
   424.4 1771.88   444.4 1776.17   514.3 1783.42   524.3 1783.64   544.3 1782.71
   554.3 1782.71   564.3 1785.38   574.3 1791.79   584.3 1799.69   604.3 1814.10
   614.3 1824.50   644.3 1840.19   694.2 1868.16   714.2 1884.85   764.2 1910.41
#Mann= 3 , 0 , 0
       0     0.1       0   383.3   0.045       0   398.3     0.1       0
Bank Sta=   383.3,   398.3
Exp/Cntr=0.3,0.1

Type RM Length L Ch R = 1 ,8469.4,602.2,603.6,605
XS GIS Cut Line= 3
     1914446.718      321354.632     1914736.280      321399.874
     1915269.464      321378.327
#Sta/Elev= 30
       0 1846.21    48.8 1833.29    68.4 1825.15   127.0 1809.36   136.8 1806.48
   146.5 1802.51   166.1 1798.65   214.9 1791.42   234.5 1787.00   254.0 1784.42
   263.8 1782.07   312.8 1763.80   322.7 1762.49   366.2 1762.42   381.2 1762.40
   421.5 1762.02   431.4 1762.61   471.0 1770.81   480.8 1772.19   520.4 1772.84
   540.1 1775.13   569.8 1781.74   579.6 1785.87   629.1 1815.16   638.9 1825.30
   708.1 1865.06   718.0 1876.08   787.2 1914.63   797.0 1924.89   826.7 1940.42
#Mann= 3 , 0 , 0
       0     0.1       0   366.2   0.045       0   381.2     0.1       0
Bank Sta=   366.2,   381.2
Exp/Cntr=0.3,0.1

Type RM Length L Ch R = 1 ,7866,7902.9,7865.6,7828.2
XS GIS Cut Line= 2
     1914467.211      321935.275     1915073.676      321956.174
#Sta/Elev= 30
       0 1815.55    39.8 1806.35    49.7 1802.29    59.7 1799.16   139.3 1778.98
   149.2 1777.81   179.1 1777.24   189.0 1775.80   208.9 1769.46   228.8 1758.38
   238.8 1754.88   248.7 1752.37   258.6 1751.34   268.6 1751.19   338.2 1751.20
   348.2 1751.37   378.0 1754.44   388.0 1752.76   407.9 1746.32   417.8 1743.82
   427.8 1742.84   435.1 1743.00   450.1 1744.47   457.6 1746.09   477.5 1752.45
   527.2 1770.83   537.2 1776.28   547.1 1783.10   577.0 1796.95   606.8 1812.35
#Mann= 3 , 0 , 0
       0     0.1       0   435.1   0.045       0   450.1     0.1       0
Bank Sta=   435.1,   450.1
Exp/Cntr=0.3,0.1